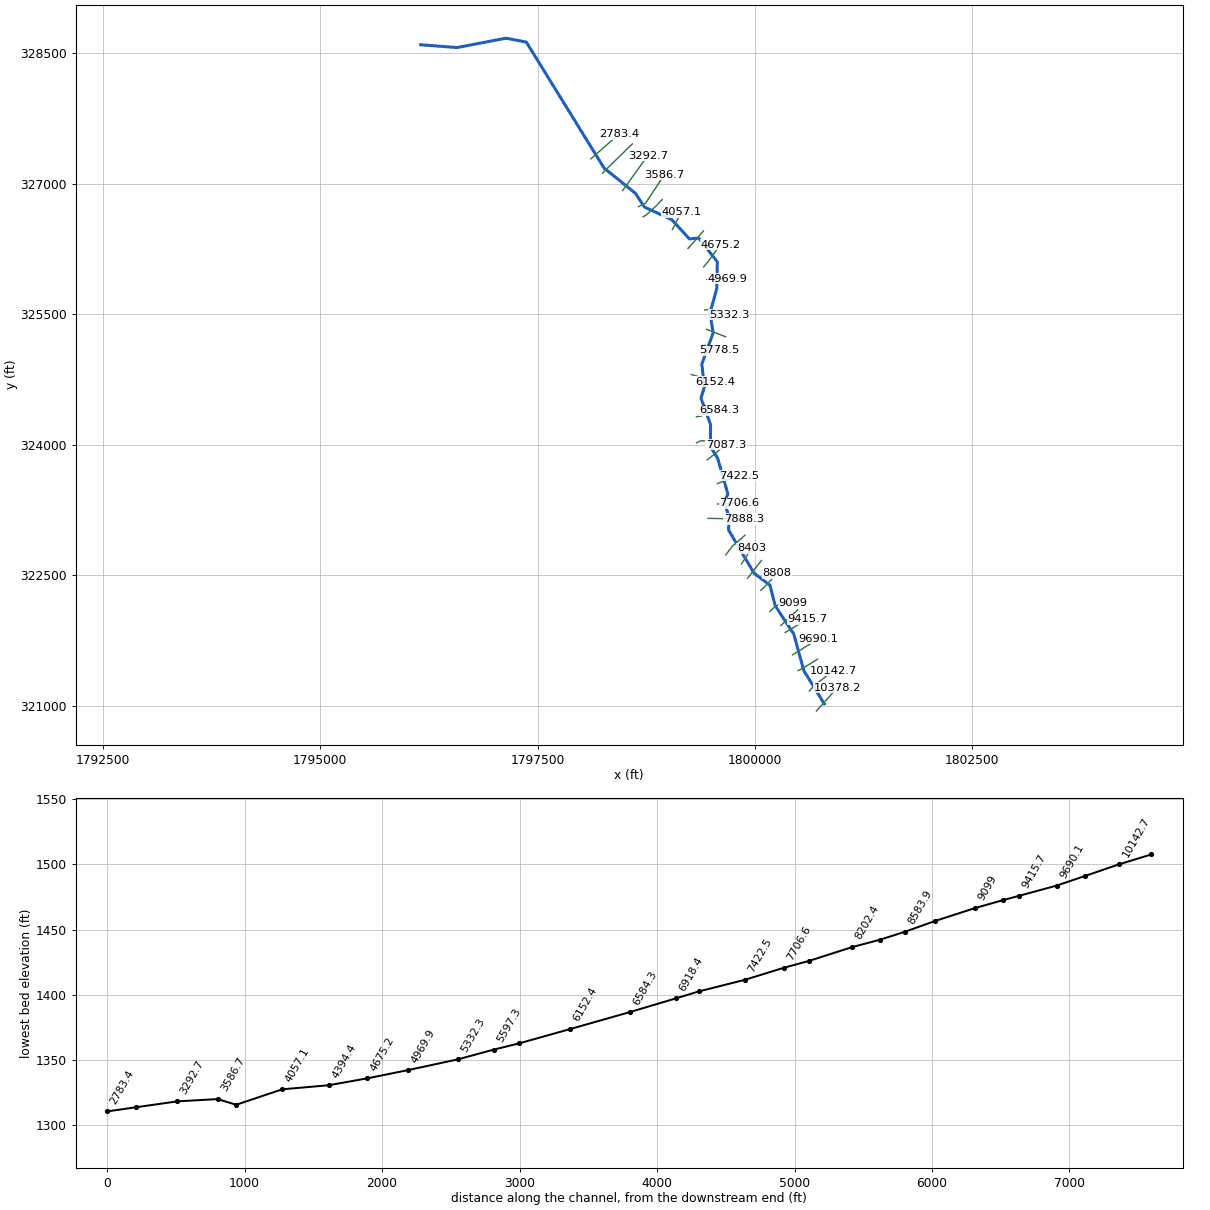
--- MATTSCK.prj (project) ---

Proj Title=MATTSCK
Current Plan=p01
Default Exp/Contr=0,0
English Units
Geom File=g01
Flow File=f01
Plan File=p01
BEGIN DESCRIPTION:
END DESCRIPTION:
DSS Export Rating Curves= 0
DSS Export Rating Curve Sorted= 0
DSS Export Volume Flow Curves= 0
DXF OffsetX= 0
DXF OffsetY= 0
DXF ScaleX= 0
DXF ScaleY= 0

--- MATTSCK.p01 (plan) ---

Plan Title=Floodplain
Program Version=4.00
Geom File=g01
Flow File=f01
K Sum by GR=0
Std Step Tol=0.01
Critical Tol=0.01
Num of Std Step Trials=20
Max Error Tol=0.3
Flow Tol Ratio=0.001
Split Flow NTrial=30
Split Flow Tol=0.02
Split Flow Ratio=0.02
Log Output Level=0
Friction Slope Method=1
Unsteady Friction Slope Method=2
Unsteady Bridges Friction Slope Method=1
Global Log Level=0
CheckData=False
Run HTab=0
Run UNet=0
Run PostProcess=0
UNET Theta=0
UNET Theta Warmup=0
UNET ZTol=0
UNET ZSATol=0
UNET MxIter=0
UNET MaxInSteps=0
UNET DtIC=0
UNET DtMin=0
UNET MaxCRTS=0
UNET WFStab=0
UNET SFStab=0
UNET WFX=0
UNET SFX=0
UNET DSS MLevel=0
UNET DZMax Abort=0
UNET Convert EG Bridges=0
UNET Use Existing IB Tables=0
UNET Froude Limit=0
UNET Froude Power=0
Write IC File=0
Echo Input=False
Echo Output=False
Write Detailed=0

--- MATTSCK.f01 (steady flow) ---

Flow Title=NFF Regression Equation
Program Version=4.00
Number of Profiles=1
Profile Names=P100yr
River Rch & RM=MATTSCK,Main      ,10378.2
896.6549
River Rch & RM=MATTSCK,Main      ,7888.3
990.5840
River Rch & RM=MATTSCK,Main      ,4969.9
1098.878
River Rch & RM=MATTSCK,Main      ,4675.2
1222.753
River Rch & RM=MATTSCK,Main      ,3292.7
1254.500
River Rch & RM=MATTSCK,Main      ,592.5
1385.026
Boundary for River Rch & Prof#=MATTSCK,Main      ,1
Up Type=0
Dn Type=3
Dn Slope=0.019628

--- MATTSCK.g01 (geometry) ---

Geom Title=USGS 10m DEM
Program Version=4.10

River Reach=MATTSCK         ,Main
Reach XY= 30
     1800797.573      321020.912     1800562.701      321401.041
     1800446.459      321823.477     1800232.049      322150.908
     1800172.153      322385.457     1799988.699      322525.173
     1799696.459      323020.873     1799702.535      323178.859
     1799644.376      323336.238     1799688.646      323432.592
     1799572.327      323841.447     1799487.397      323982.421
     1799488.993      324233.721      1799378.75      324537.453
     1799419.549      324666.794     1799388.656      324926.432
     1799518.864       325287.76     1799483.057      325515.317
     1799560.068      325793.585     1799567.692      326103.732
     1799351.428      326378.614     1799246.512      326367.404
     1799043.713      326589.131     1798727.849      326735.242
     1798623.682      326893.662     1798264.728      327182.574
     1797370.954      328630.961     1797137.742      328675.674
     1796572.686      328568.274     1796156.736      328600.302

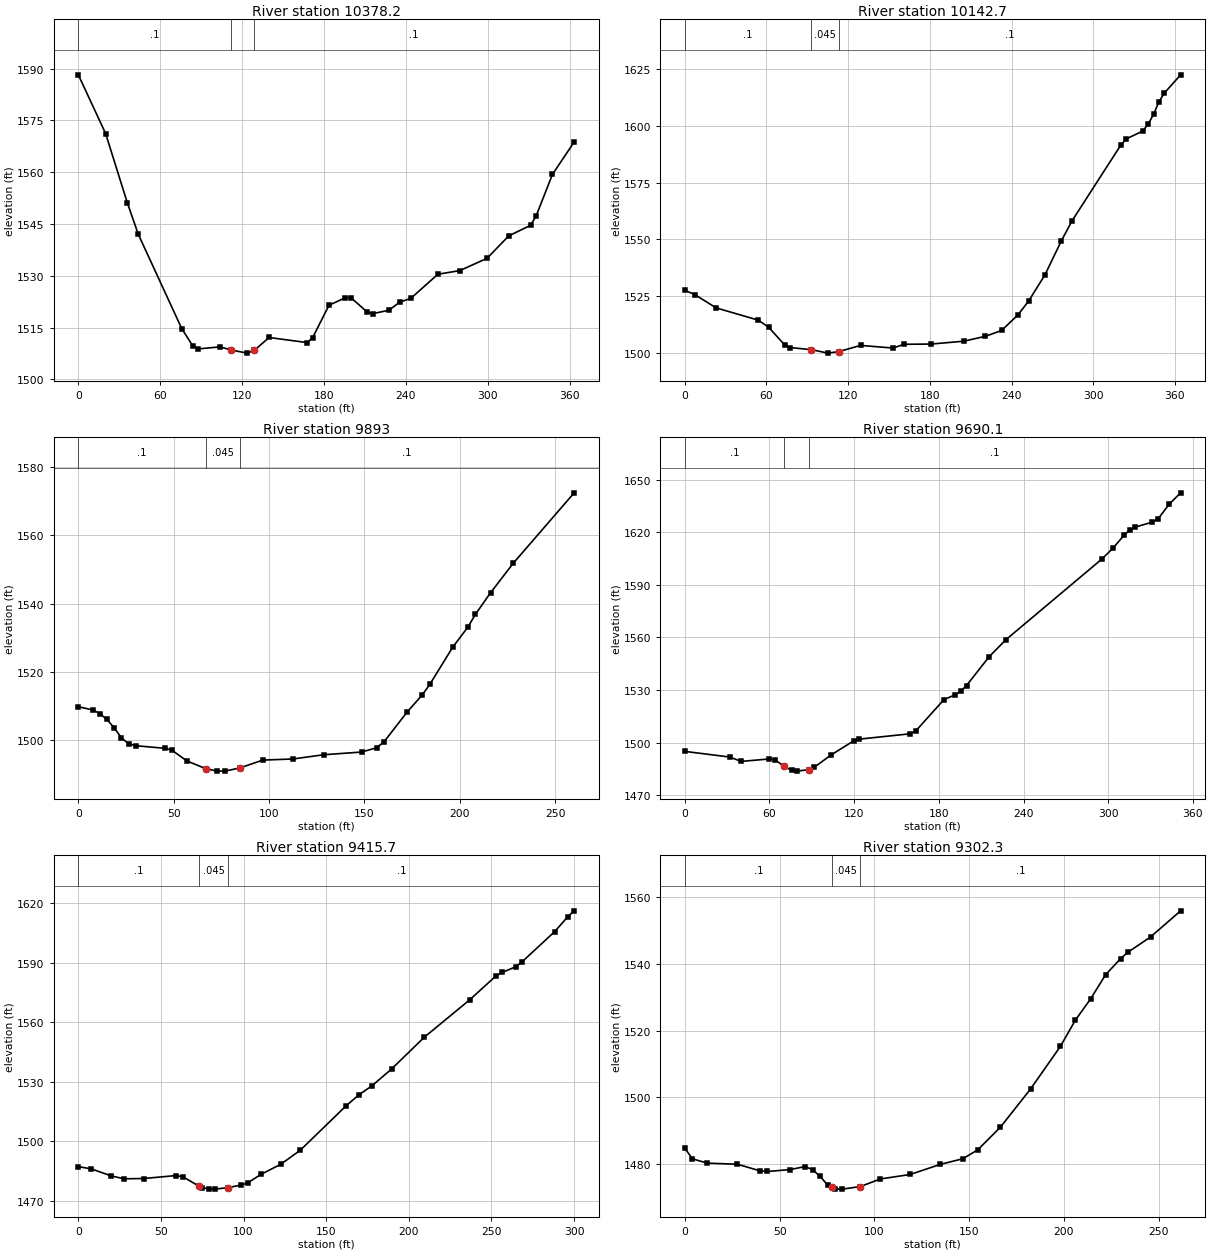
Type RM Length L Ch R = 1 ,10378.2 ,238.9,235.5,230.8
XS GIS Cut Line= 2
     1800706.567      320939.076     1800950.056      321208.608
#Sta/Elev= 30
       0 1588.22      20  1571.2    35.9 1551.14    43.9 1542.04    75.8 1514.66
    83.8 1509.71    87.8 1508.82   103.8 1509.41   111.8 1508.52   123.7  1507.6
   128.9 1508.39   139.7 1512.13   167.6 1510.65   171.6 1512.04   183.6 1521.47
   195.6 1523.65   199.6  1523.7   211.6  1519.5   215.5 1519.03   227.5 1520.03
   235.5 1522.38   243.5 1523.45   263.4 1530.46   279.4  1531.5   299.4 1535.07
   315.3 1541.57   331.3 1544.63   335.3  1547.3   347.3 1559.38   363.2 1568.76
#Mann= 3 , 0 , 0
       0      .1       0   111.8    .045       0   128.9      .1       0
Bank Sta=111.8,128.9
XS Rating Curve= 0 ,0
Exp/Cntr=0.3,0.1

Type RM Length L Ch R = 1 ,10142.7 ,249.2,249.7,248.6
XS GIS Cut Line= 3
     1800625.838      321168.243     1800670.108      321221.628
     1800901.879       321403.92
#Sta/Elev= 30
       0 1527.67     7.7 1525.58    23.1 1519.87    53.9  1514.5    61.6 1511.36
    73.3 1503.62    77.3 1502.43      93 1501.51   105.2 1499.98   113.2 1500.67
   129.1 1503.37     153 1502.22     161 1503.87   180.9 1503.97   204.8 1505.22
   220.8 1507.37   232.7 1509.96   244.7 1516.78   252.6 1522.93   264.6 1534.47
   276.6  1549.4   284.5 1558.23   320.4 1591.62   324.4 1594.24   336.3 1597.65
   340.3 1600.65   344.3 1605.02   348.3 1610.58   352.3 1614.41   364.2  1622.4
#Mann= 3 , 0 , 0
       0      .1       0      93    .045       0   113.2      .1       0
Bank Sta=93,113.2
XS Rating Curve= 0 ,0
Exp/Cntr=0.3,0.1

Type RM Length L Ch R = 1 ,9893    ,204.2,202.9,199.9
XS GIS Cut Line= 3
     1800496.931       321403.92     1800541.202      321424.753
      1800720.89       321535.43
#Sta/Elev= 30
       0 1509.83     7.5 1508.89    11.3 1507.81      15  1506.1    18.8 1503.64
    22.6  1500.7    26.4 1498.97    30.1 1498.41    45.2 1497.66    48.9 1497.16
    56.9 1493.95    66.7  1491.7    72.8 1490.98    76.8 1490.96    84.8 1491.91
    96.7 1494.19   112.6 1494.52   128.6 1495.76   148.5 1496.55   156.4  1497.8
   160.4 1499.61   172.4 1508.27   180.3 1513.26   184.3 1516.37   196.3 1527.25
   204.2  1533.1   208.2 1536.87   216.2 1543.26   228.1 1551.89     260  1572.5
#Mann= 3 , 0 , 0
       0      .1       0    66.7    .045       0    84.8      .1       0
Bank Sta=66.7,84.8
XS Rating Curve= 0 ,0
Exp/Cntr=0.3,0.1

Type RM Length L Ch R = 1 ,9690.1  ,274.5,274.4,273.5
XS GIS Cut Line= 2
     1800431.827       321584.91     1800731.306      321768.503
#Sta/Elev= 30
       0 1494.97    31.9 1491.75    39.9 1489.25    59.9 1490.67    63.9 1490.24
    70.1 1486.52    75.8 1484.16    79.8 1483.72    87.8 1484.61    91.8 1485.96
   103.8 1493.03   119.8 1501.04   123.7 1501.97   159.7 1505.01   163.7 1506.69
   183.6 1524.49   191.6 1527.28   195.6 1529.33   199.6 1532.54   215.6 1548.92
   227.5 1558.66   295.4  1604.6   303.4 1610.87   311.4 1618.44   315.4 1621.31
   319.3 1622.92   331.3 1625.74   335.3 1627.55   343.3 1636.07   351.3 1642.43
#Mann= 3 , 0 , 0
       0      .1       0    70.1    .045       0    87.8      .1       0
Bank Sta=70.1,87.8
XS Rating Curve= 0 ,0
Exp/Cntr=0.3,0.1

Type RM Length L Ch R = 1 ,9415.7  ,108.4,113.3,118.1
XS GIS Cut Line= 2
     1800347.192       321841.42     1800605.004      321995.066
#Sta/Elev= 30
       0 1487.19     7.9 1486.06    19.7 1482.58    27.6 1481.06    39.5  1481.2
    59.2  1482.7    63.2 1482.12    73.2 1477.27      75 1476.55      79 1475.94
    82.9 1475.85    90.8 1476.64    98.7 1477.92   102.7 1479.09   110.6 1483.33
   122.4 1488.33   134.3 1495.44   161.9 1517.75   169.8 1523.41   177.7 1527.97
   189.6 1536.44   209.3 1552.42   236.9 1571.36   252.7 1583.36   256.7 1585.19
   264.6 1587.99   268.5 1590.46   288.3 1605.75   296.2 1613.21   300.1 1616.24
#Mann= 3 , 0 , 0
       0      .1       0    73.2    .045       0    90.8      .1       0
Bank Sta=73.2,90.8
XS Rating Curve= 0 ,0
Exp/Cntr=0.3,0.1

Type RM Length L Ch R = 1 ,9302.3  ,206.6,203.4,200.4
XS GIS Cut Line= 2
     1800299.015      321923.451     1800490.421      322101.837
#Sta/Elev= 30
       0 1484.87       4 1481.68    11.9 1480.39    27.8 1480.06    39.6  1478.1
    43.6  1477.9    55.5 1478.46    63.4 1479.36    67.4 1478.44    71.4 1476.44
    75.3 1473.87    77.7 1473.14    79.3 1472.66    83.2 1472.63    92.7 1473.41
   103.1 1475.66   118.9    1477   134.8 1480.02   146.7  1481.7   154.6 1484.38
   166.5 1491.12   182.4 1502.52   198.2 1515.29   206.1 1523.13   214.1 1529.43
     222 1536.65   229.9 1541.43   233.9 1543.41   245.8 1547.97   261.6 1555.74
#Mann= 3 , 0 , 0
       0      .1       0    77.7    .045       0    92.7      .1       0
Bank Sta=77.7,92.7
XS Rating Curve= 0 ,0
Exp/Cntr=0.3,0.1

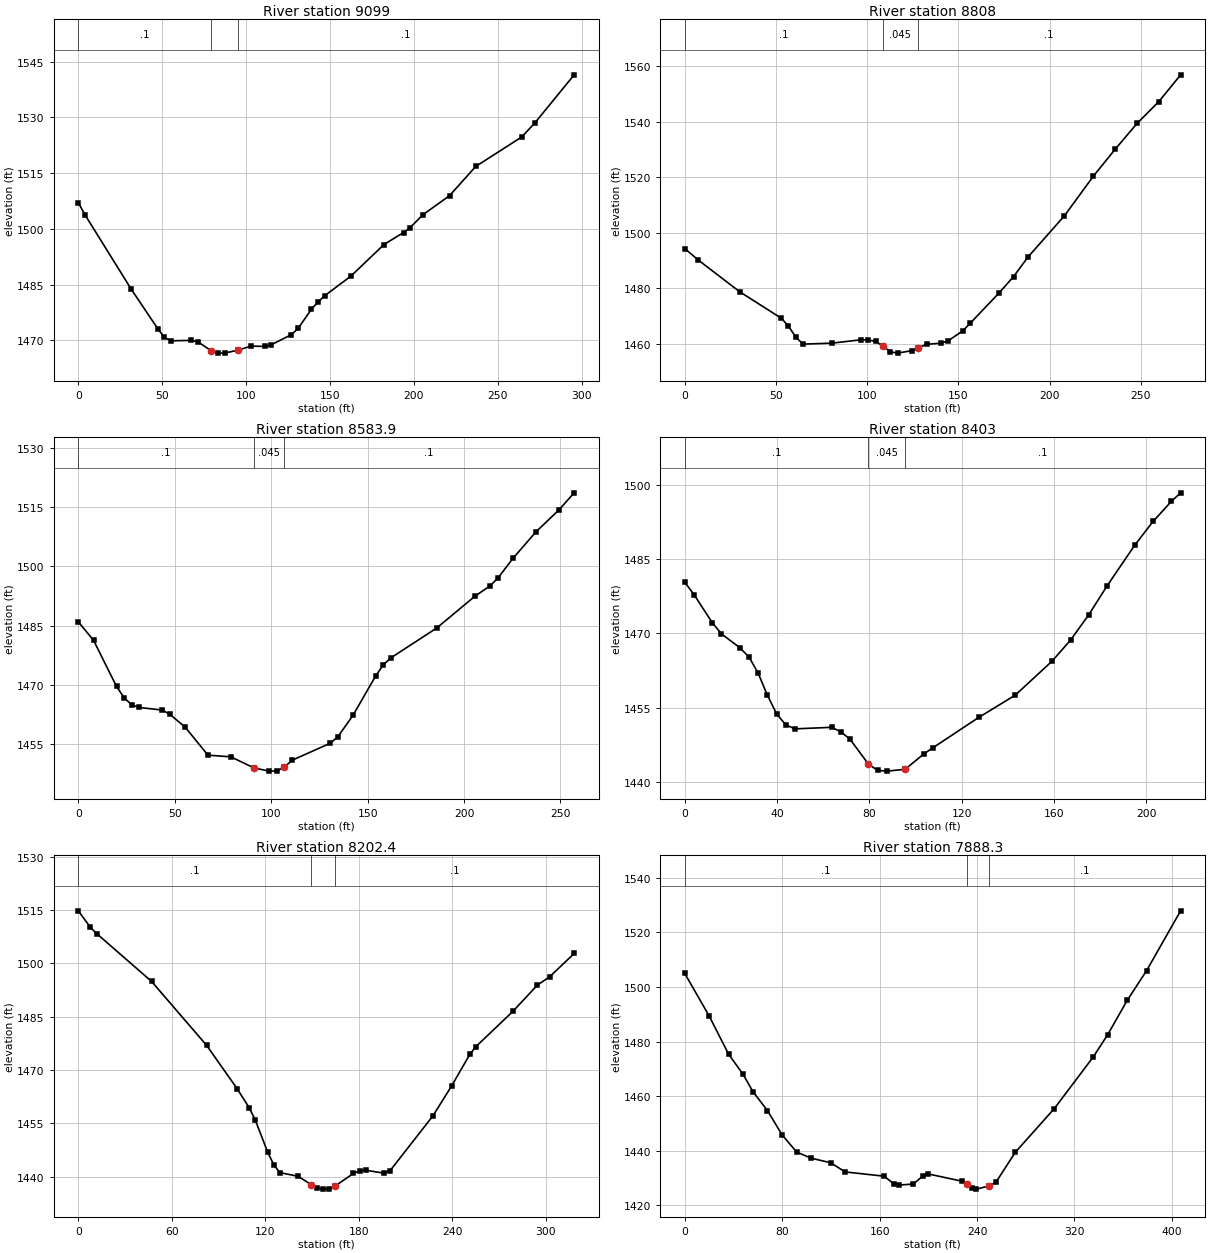
Type RM Length L Ch R = 1 ,9099    ,286.1,291,295.3
XS GIS Cut Line= 4
     1800172.713      322083.608     1800202.661      322114.858
     1800287.296      322174.753     1800435.733      322182.566
#Sta/Elev= 30
       0 1507.07     3.9 1503.85    31.5  1483.8    47.3 1473.17    51.3 1470.79
    55.2 1469.88    67.2 1469.99    71.2 1469.65    79.3 1467.15    83.2 1466.56
    87.2 1466.56    95.1 1467.36   103.1 1468.46   111.1 1468.36   115.1 1468.83
     127 1471.53     131  1473.2     139 1478.39     143 1480.39     147 1482.05
   162.6 1487.33   182.2 1495.79   193.9 1499.03   197.8 1500.36   205.6 1503.87
   221.3 1508.95   236.9 1516.81   264.3 1524.74   272.1 1528.49   295.6 1541.48
#Mann= 3 , 0 , 0
       0      .1       0    79.3    .045       0    95.1      .1       0
Bank Sta=79.3,95.1
XS Rating Curve= 0 ,0
Exp/Cntr=0.3,0.1

Type RM Length L Ch R = 1 ,8808    ,222,224.1,227
XS GIS Cut Line= 3
     1800065.942      322325.795       1800102.4      322358.347
     1800254.744      322521.108
#Sta/Elev= 30
       0 1494.29     7.5 1490.11    30.1 1478.74    52.9 1469.22    56.8  1466.4
    60.8 1462.44    64.8  1459.9    80.7 1460.24    96.6 1461.46   100.6 1461.39
   104.6 1460.84   108.6 1459.21   112.6 1457.16   116.6 1456.65   124.5 1457.55
   127.7  1458.5   132.5 1459.82   140.4 1460.23   144.4  1461.1   152.4 1464.68
   156.4 1467.36   172.3 1478.34   180.2 1484.19   188.2 1491.31   208.1 1506.09
     224 1520.39     236 1530.12   247.9 1539.35   259.9 1547.24   271.8 1556.85
#Mann= 3 , 0 , 0
       0      .1       0   108.6    .045       0   127.7      .1       0
Bank Sta=108.6,127.7
XS Rating Curve= 0 ,0
Exp/Cntr=0.3,0.1

Type RM Length L Ch R = 1 ,8583.9  ,178,180.9,181.8
XS GIS Cut Line= 2
     1799916.202       322466.42     1800073.754      322669.545
#Sta/Elev= 30
       0 1485.96     7.9 1481.28    19.8 1469.62    23.7  1466.8    27.7 1464.95
    31.6 1464.31    43.5 1463.65    47.5 1462.56    55.4 1459.33    67.2 1452.25
    79.1 1451.82      91 1449.04    98.9 1448.21   102.8 1448.24   106.8 1449.18
   110.7 1450.92   130.5 1455.24   134.5 1456.85   142.4  1462.3   154.2 1472.29
   158.2 1475.13   162.2 1476.89   185.9 1484.42   205.6 1492.42   213.6  1495.1
   217.5 1496.99   225.4 1502.02   237.3 1508.72   249.2 1514.26   257.1 1518.58
#Mann= 3 , 0 , 0
       0      .1       0      91    .045       0   106.8      .1       0
Bank Sta=91,106.8
XS Rating Curve= 0 ,0
Exp/Cntr=0.3,0.1

Type RM Length L Ch R = 1 ,8403    ,207.5,200.6,193.5
XS GIS Cut Line= 2
     1799844.588      322630.483     1799960.473      322811.472
#Sta/Elev= 30
       0 1480.33       4 1477.84    11.9 1472.17    15.9 1469.89    23.9 1467.08
    27.9 1465.17    31.8 1461.94    35.8 1457.48    39.8 1453.72    43.8 1451.48
    47.8 1450.69    63.7    1451    67.7 1450.07    71.6  1448.6    79.6 1443.55
    83.6 1442.28    87.6 1442.14    95.5 1442.51   103.5 1445.58   107.5 1446.85
   127.4    1453   143.3 1457.53   159.2 1464.39   167.2 1468.64   175.1 1473.77
   183.1 1479.66     195 1487.82     203 1492.66   210.9 1496.69   214.9 1498.42
#Mann= 3 , 0 , 0
       0      .1       0    79.6    .045       0    95.5      .1       0
Bank Sta=79.6,95.5
XS Rating Curve= 0 ,0
Exp/Cntr=0.3,0.1

Type RM Length L Ch R = 1 ,8202.4  ,330.7,314.1,297.2
XS GIS Cut Line= 3
     1799664.032      322733.202     1799739.119      322833.608
     1799884.952       322959.91
#Sta/Elev= 30
       0 1514.75     7.8 1510.07    11.8 1508.34      47 1494.92    82.3 1476.97
   101.9 1464.79   109.7 1459.41   113.6 1455.95   121.5 1446.98   125.4 1443.44
   129.3 1441.19   141.1 1440.15   149.3 1437.84   152.9 1436.94   156.9 1436.54
   160.8 1436.64   164.8 1437.39   176.6 1440.96   180.5 1441.67   184.4 1441.86
   196.2 1441.03   200.2 1441.76   227.7 1457.17   239.6 1465.52   251.4 1474.47
   255.3 1476.62   278.9 1486.46   294.7 1493.88   302.6 1496.22   318.3 1502.76
#Mann= 3 , 0 , 0
       0      .1       0   149.3    .045       0   164.8      .1       0
Bank Sta=149.3,164.8
XS Rating Curve= 0 ,0
Exp/Cntr=0.3,0.1

Type RM Length L Ch R = 1 ,7888.3  ,180.9,181.7,182.6
XS GIS Cut Line= 2
     1799462.209      323154.209     1799869.327       323147.41
#Sta/Elev= 30
       0 1504.93      20 1489.37    35.9 1475.42    47.9 1467.96    55.9 1461.68
    67.9  1454.7    79.8 1445.89    91.8 1439.54   103.8 1437.26   119.8 1435.61
   131.7 1432.24   163.7 1430.68   171.6 1427.92   175.6 1427.42   187.6 1427.81
   195.6 1430.76   199.6 1431.53   227.5 1428.86   231.5 1427.84   235.5 1426.33
   239.5 1425.94   250.2 1427.15   255.5 1428.43   271.4 1439.42   303.4 1455.41
   335.3 1474.27   347.3 1482.51   363.3 1495.06   379.2 1505.95   407.2 1527.88
#Mann= 3 , 0 , 0
       0      .1       0   231.5    .045       0   250.2      .1       0
Bank Sta=231.5,250.2
XS Rating Curve= 0 ,0
Exp/Cntr=0.3,0.1

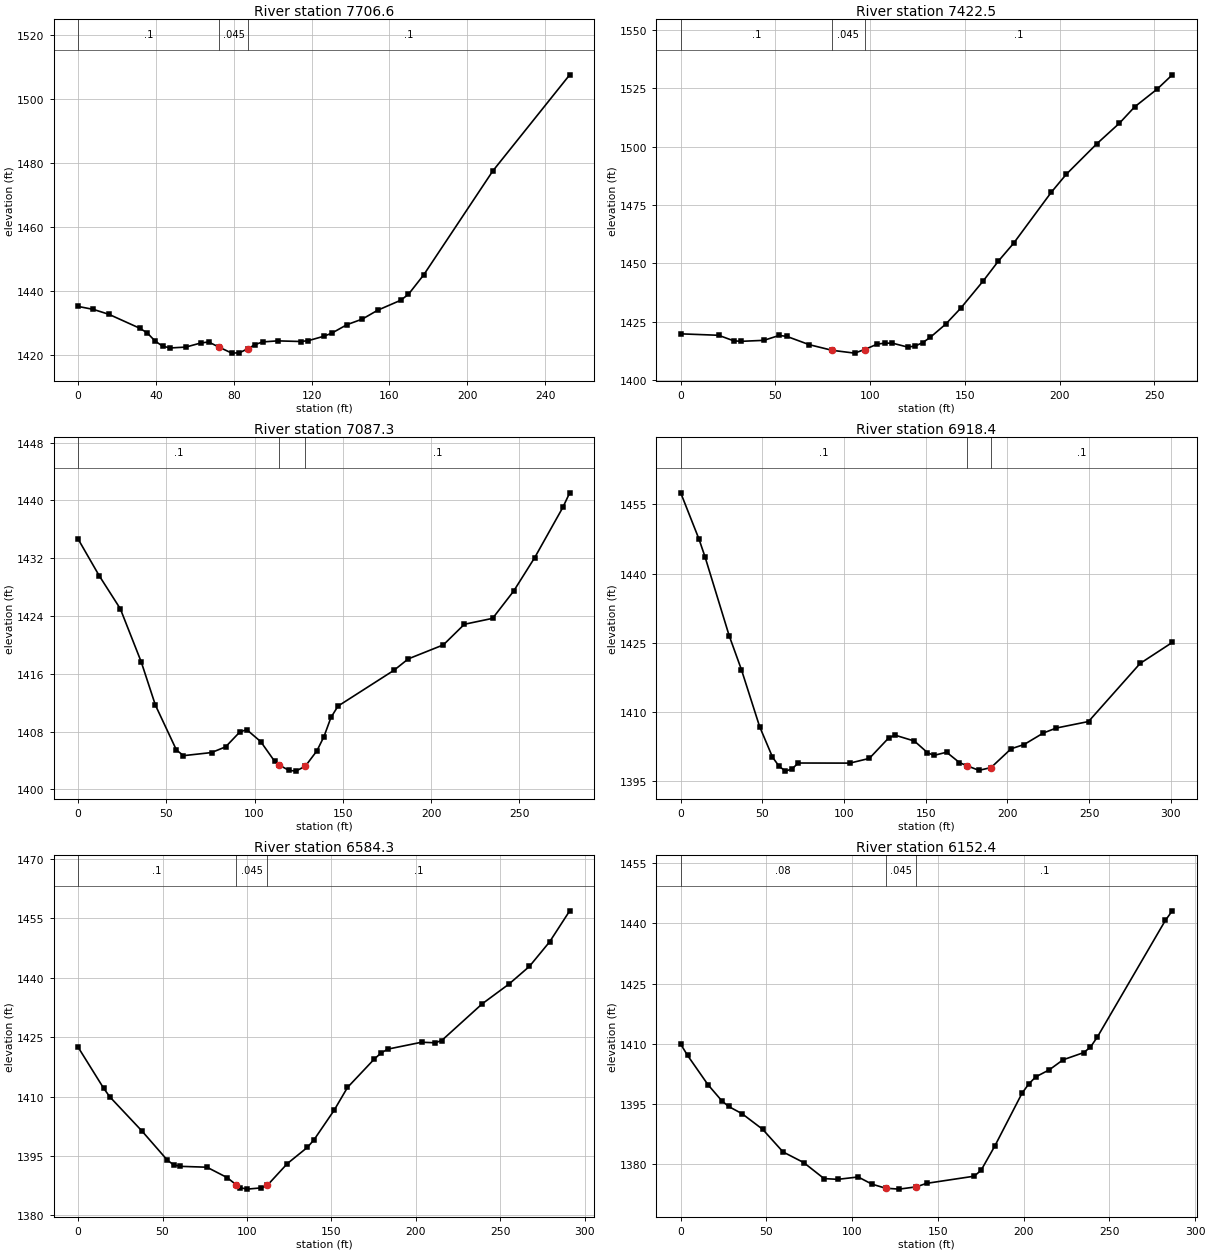
Type RM Length L Ch R = 1 ,7706.6  ,276.1,284.1,291.2
XS GIS Cut Line= 2
     1799569.848      323319.285     1799822.452      323325.795
#Sta/Elev= 30
       0  1435.3     7.9 1434.36    15.8 1432.84    31.6 1428.51    35.5 1427.04
    39.5 1424.53    43.4 1422.88    47.4 1422.33    55.3 1422.59    63.2  1423.9
    67.1 1424.19    72.5 1422.56      79 1420.71    82.9 1420.82    87.5 1422.15
    90.8 1423.33    94.8 1424.21   102.6 1424.54   114.5 1424.34   118.4 1424.62
   126.3 1425.98   130.3 1426.92   138.2  1429.6   146.1 1431.35     154 1434.12
   165.8 1437.22   169.8 1439.08   177.7  1445.2   213.2 1477.65   252.7 1507.66
#Mann= 3 , 0 , 0
       0      .1       0    72.5    .045       0    87.5      .1       0
Bank Sta=72.5,87.5
XS Rating Curve= 0 ,0
Exp/Cntr=0.3,0.1

Type RM Length L Ch R = 1 ,7422.5  ,327.2,335.2,342.6
XS GIS Cut Line= 2
     1799568.546      323554.962     1799812.036      323644.805
#Sta/Elev= 30
       0 1419.74      20 1419.12      28 1416.74    31.9 1416.53    43.9 1416.95
    51.9 1419.03    55.9 1418.68    67.9 1415.08    79.9 1412.68    91.8 1411.47
    97.1 1413.02   103.8 1415.35   107.8 1415.75   111.8 1415.74   119.8 1414.06
   123.8 1414.52   127.8    1416   131.8 1418.28   139.8 1423.83   147.7 1430.62
   159.7 1442.42   167.7 1450.93   175.7 1458.53   195.6 1480.41   203.6 1488.19
   219.6 1501.17   231.6 1510.04   239.6 1517.01   251.6 1524.71   259.5 1530.77
#Mann= 3 , 0 , 0
       0      .1       0    79.9    .045       0    97.1      .1       0
Bank Sta=79.9,97.1
XS Rating Curve= 0 ,0
Exp/Cntr=0.3,0.1

Type RM Length L Ch R = 1 ,7087.3  ,184.5,168.8,153
XS GIS Cut Line= 3
     1799450.056      323827.097     1799485.213      323853.139
     1799666.202      324002.878
#Sta/Elev= 30
       0 1434.65    11.9  1429.6    23.9 1425.01    35.8 1417.63    43.8 1411.67
    55.7 1405.47    59.7 1404.68    75.6 1405.11    83.6  1405.9    91.5 1407.92
    95.5 1408.29   103.5 1406.62   111.4 1403.89   113.8 1403.41   119.4 1402.65
   123.4 1402.54   128.8 1403.23   135.3 1405.34   139.3  1407.3   143.3 1409.97
   147.3 1411.54   179.1 1416.51   187.1 1418.07     207 1420.01   218.9 1422.86
   234.9 1423.68   246.8 1427.44   258.8  1432.1   274.7 1439.03   278.6 1441.05
#Mann= 3 , 0 , 0
       0      .1       0   113.8    .045       0   128.8      .1       0
Bank Sta=113.8,128.8
XS Rating Curve= 0 ,0
Exp/Cntr=0.3,0.1

Type RM Length L Ch R = 1 ,6918.4  ,317.5,334.2,351.8
XS GIS Cut Line= 3
     1799327.661       324022.41     1799370.629      324044.545
     1799623.233      324051.055
#Sta/Elev= 30
       0 1457.53    11.2 1447.48    14.9 1443.63    29.7 1426.51    37.2 1419.15
    48.3 1406.84    56.2  1400.2    60.2 1398.23    64.1 1397.16    68.1 1397.62
      72 1398.92   103.6  1398.9   115.5 1399.92   127.3 1404.34   131.2 1404.97
   143.1 1403.68     151  1401.2   154.9 1400.56   162.8 1401.26   170.7 1399.01
     175 1398.37   182.6 1397.33     190 1397.93   202.3 1402.01   210.2 1402.92
   222.1 1405.44     230 1406.51   249.7 1407.92   281.3 1420.52     301 1425.08
#Mann= 3 , 0 , 0
       0      .1       0     175    .045       0     190      .1       0
Bank Sta=175,190
XS Rating Curve= 0 ,0
Exp/Cntr=0.3,0.1

Type RM Length L Ch R = 1 ,6584.3  ,455.2,431.8,405.8
XS GIS Cut Line= 4
     1799326.358      324321.889     1799382.348      324329.701
     1799461.775      324401.316     1799589.379       324397.41
#Sta/Elev= 30
       0 1422.46    15.1 1412.12    18.8 1409.92    37.7 1401.36    52.8 1393.98
    56.5 1392.79    60.5  1392.4    76.3 1392.18    88.2 1389.57    93.5 1387.79
    96.1    1387   100.1 1386.65     108 1386.95     112 1387.59   123.9  1393.1
   135.8  1397.2   139.7 1399.11   151.6 1406.55   159.5  1412.3   175.4 1419.48
   179.4 1421.01   183.4 1421.98   203.4 1423.72   211.4 1423.58   215.3 1424.15
   239.3 1433.42   255.2 1438.42   267.2 1442.84   279.2 1449.05   291.1 1456.88
#Mann= 3 , 0 , 0
       0      .1       0    93.5    .045       0     112      .1       0
Bank Sta=93.5,112
XS Rating Curve= 0 ,0
Exp/Cntr=0.3,0.1

Type RM Length L Ch R = 1 ,6152.4  ,374.3,373.9,373.3
XS GIS Cut Line= 2
     1799266.463      324808.868     1799541.202      324726.837
#Sta/Elev= 30
       0 1409.86       4 1407.06    15.9 1399.76    23.9 1395.78    27.9 1394.34
    35.8 1392.52    47.8 1388.63    59.7 1382.98    71.7 1380.34    83.6 1376.34
    91.6 1376.15   103.5 1376.74   111.5 1374.96   119.5 1373.94   127.4 1373.71
   137.4 1374.28   143.4 1375.15   171.2 1376.94   175.2 1378.42   183.2 1384.47
   199.1 1397.66   203.1    1400   207.1 1401.72     215 1403.48     223 1405.97
     235 1407.76   238.9 1409.11   242.9 1411.58   282.7 1440.77   286.7 1443.13
#Mann= 3 , 0 , 0
       0     .08       0   119.5    .045       0   137.4      .1       0
Bank Sta=119.5,137.4
XS Rating Curve= 0 ,0
Exp/Cntr=0.3,0.1

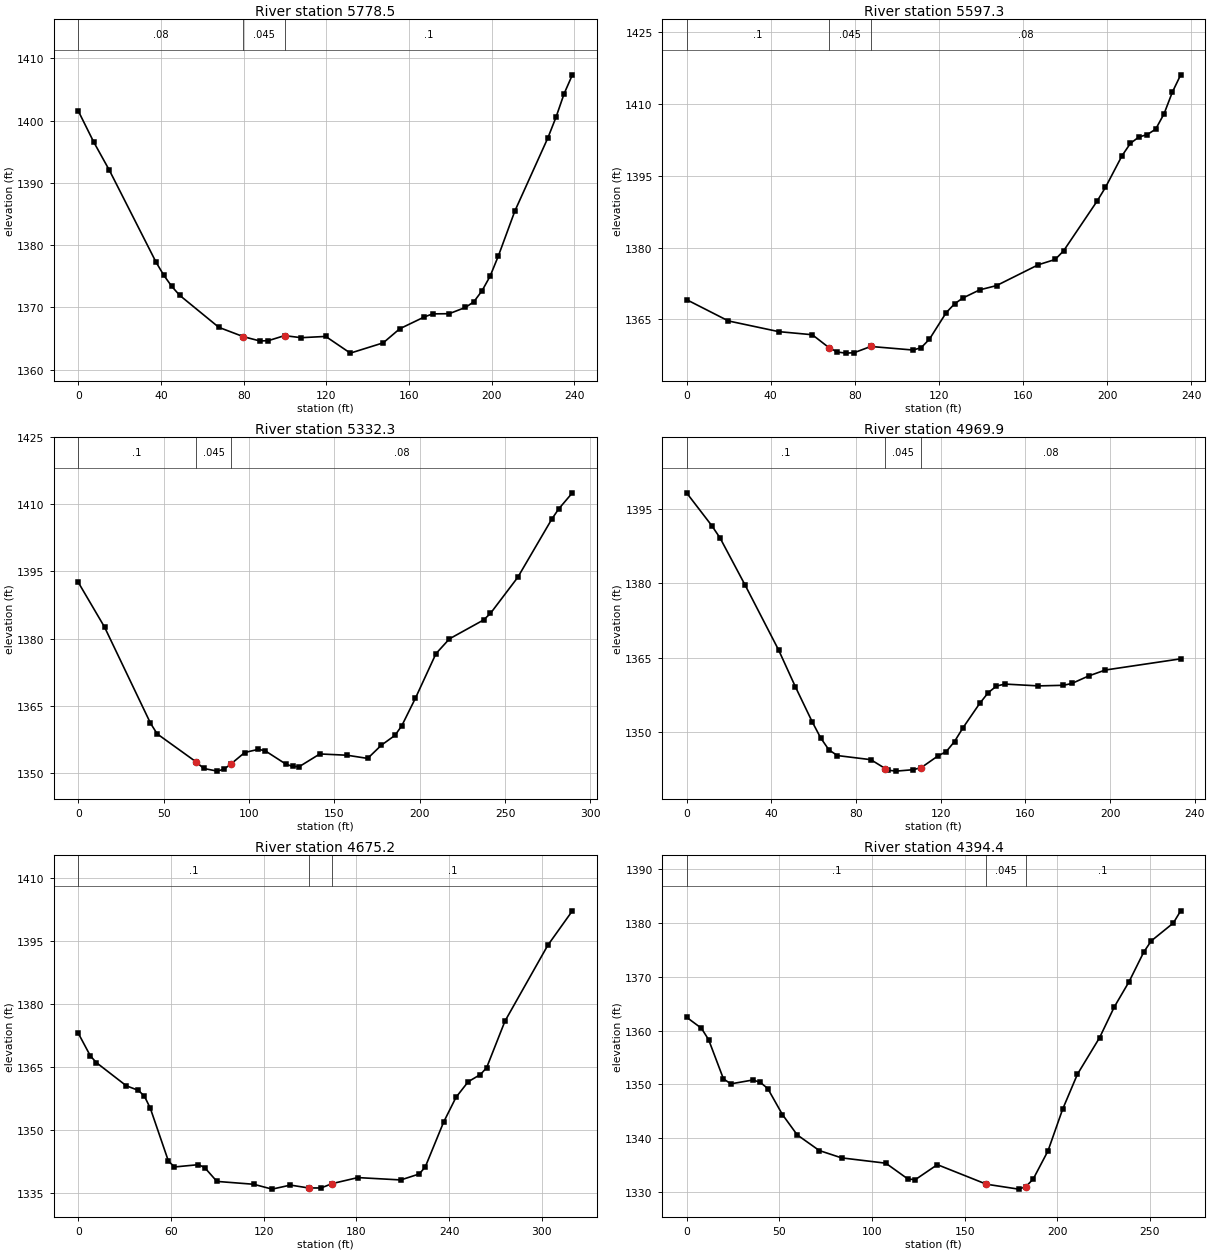
Type RM Length L Ch R = 1 ,5778.5  ,182,181.2,179.8
XS GIS Cut Line= 3
     1799357.608      325138.295     1799421.411      325143.503
     1799586.775      325086.212
#Sta/Elev= 30
       0 1401.55     7.5 1396.54    15.1 1391.99    37.7 1377.22    41.4 1375.15
    45.2 1373.39      49 1371.96      68  1366.8    79.9  1365.3    87.9 1364.61
    91.9 1364.66    99.8 1365.47   107.8 1365.14   119.7 1365.34   131.6 1362.66
   147.5 1364.31   155.5 1366.57   167.4 1368.47   171.4 1368.96   179.4 1368.99
   187.3    1370   191.3 1370.89   195.3 1372.67   199.2 1375.01   203.2 1378.26
   211.2 1385.49   227.1 1397.18   231.1 1400.55     235 1404.31     239 1407.34
#Mann= 3 , 0 , 0
       0     .08       0    79.9    .045       0    99.8      .1       0
Bank Sta=79.9,99.8
XS Rating Curve= 0 ,0
Exp/Cntr=0.3,0.1

Type RM Length L Ch R = 1 ,5597.3  ,259.1,265,266.5
XS GIS Cut Line= 2
     1799443.546      325328.399     1799662.296      325242.462
#Sta/Elev= 30
       0 1369.12    19.9 1364.67    43.8 1362.44    59.8 1361.79    67.7  1359.1
    71.7 1358.18    75.7 1357.95    79.7 1358.04    87.6 1359.34   107.6  1358.6
   111.5 1359.06   115.5 1360.86   123.5 1366.42   127.5 1368.26   131.4 1369.46
   139.4 1371.16   147.4 1372.05   167.3 1376.41   175.3 1377.51   179.3 1379.31
   195.2 1389.67   199.2 1392.55   207.1 1399.18   211.1 1401.77   215.1 1403.08
   219.1 1403.59   223.1 1404.73   227.1 1407.95     231 1412.43     235 1416.07
#Mann= 3 , 0 , 0
       0      .1       0    67.7    .045       0    87.6     .08       0
Bank Sta=67.7,87.6
XS Rating Curve= 0 ,0
Exp/Cntr=0.3,0.1

Type RM Length L Ch R = 1 ,5332.3  ,357.9,362.4,369.5
XS GIS Cut Line= 3
     1799421.411      325551.055     1799482.608      325557.566
     1799701.358      325493.764
#Sta/Elev= 30
       0 1392.59    15.4 1382.58    42.3 1361.11    46.2 1358.72    68.9 1352.49
    73.5 1350.98    81.5 1350.39    85.5 1350.85    89.5 1352.01    97.5 1354.55
   105.5 1355.26   109.5 1354.93   121.5 1351.98   125.5 1351.43   129.5 1351.41
   141.5 1354.23   157.5 1353.94   169.5 1353.23   177.5 1356.18   185.5 1358.38
   189.5 1360.54   197.5 1366.71   209.5 1376.64   217.4 1379.95   237.4 1384.17
   241.4 1385.63   257.4 1393.69   277.4 1406.74   281.4 1408.99   289.4 1412.58
#Mann= 3 , 0 , 0
       0      .1       0    68.9    .045       0    89.5     .08       0
Bank Sta=68.9,89.5
XS Rating Curve= 0 ,0
Exp/Cntr=0.3,0.1

Type RM Length L Ch R = 1 ,4969.9  ,273.3,294.7,314.1
XS GIS Cut Line= 2
     1799447.452      325901.316     1799680.525      325911.733
#Sta/Elev= 30
       0 1398.27    11.9 1391.65    15.8 1389.17    27.7 1379.61    43.5 1366.53
    51.4 1359.13    59.3  1352.1    63.3 1348.85    67.2 1346.43    71.2 1345.28
      87 1344.45    93.8 1342.66    94.9 1342.34    98.9 1342.14   106.8 1342.42
   110.7 1342.82   118.6 1345.18   122.6 1346.08   126.5 1348.11   130.5 1350.88
   138.4  1355.8   142.4 1357.95   146.3  1359.3   150.3  1359.7   166.1 1359.33
   177.9 1359.45   181.9 1359.82   189.8 1361.33   197.7 1362.53   233.3 1364.79
#Mann= 3 , 0 , 0
       0      .1       0    93.8    .045       0   110.7     .08       0
Bank Sta=93.8,110.7
XS Rating Curve= 0 ,0
Exp/Cntr=0.3,0.1

Type RM Length L Ch R = 1 ,4675.2  ,287.7,280.8,279.3
XS GIS Cut Line= 3
      1799408.39      326045.847     1799456.567      326101.837
       1799602.4      326299.753
#Sta/Elev= 30
       0 1373.04     7.8 1367.65    11.7 1366.03    31.1  1360.5    38.9 1359.41
    42.8 1358.03    46.6 1355.17    58.3 1342.59    62.2 1341.15    77.8  1341.7
    81.8    1341    89.7 1337.71   113.5 1337.03   125.4 1335.87   137.3 1336.83
   149.2 1336.14   157.1 1336.15   164.3 1337.19   180.9 1338.62   208.7 1338.06
   220.6 1339.48   224.5 1341.14   236.4 1351.85   244.4 1357.75   252.3 1361.47
   260.2 1363.19   264.2  1364.8   276.1 1375.92   303.8 1393.99   319.7  1402.2
#Mann= 3 , 0 , 0
       0      .1       0   149.2    .045       0   164.3      .1       0
Bank Sta=149.2,164.3
XS Rating Curve= 0 ,0
Exp/Cntr=0.3,0.1

Type RM Length L Ch R = 1 ,4394.4  ,325.2,337.3,342.7
XS GIS Cut Line= 3
     1799230.004      326259.389     1799297.713      326332.305
     1799407.088      326458.608
#Sta/Elev= 30
       0 1362.47       8 1360.43    11.9  1358.3    19.9 1351.03    23.9 1350.11
    35.8 1350.83    39.8 1350.38    43.8 1349.24    51.7 1344.42    59.7 1340.64
    71.6 1337.74    83.6 1336.38   107.5 1335.39   119.4 1332.46   123.4 1332.34
   135.3 1335.12   161.8 1331.49   179.1 1330.58     183 1331.02     187 1332.44
     195 1337.68   202.9 1345.41   210.9 1351.91   222.8 1358.66   230.8  1364.4
   238.7 1369.04   246.7 1374.58   250.7 1376.63   262.6 1379.94   266.6 1382.21
#Mann= 3 , 0 , 0
       0      .1       0   161.8    .045       0     183      .1       0
Bank Sta=161.8,183
XS Rating Curve= 0 ,0
Exp/Cntr=0.3,0.1

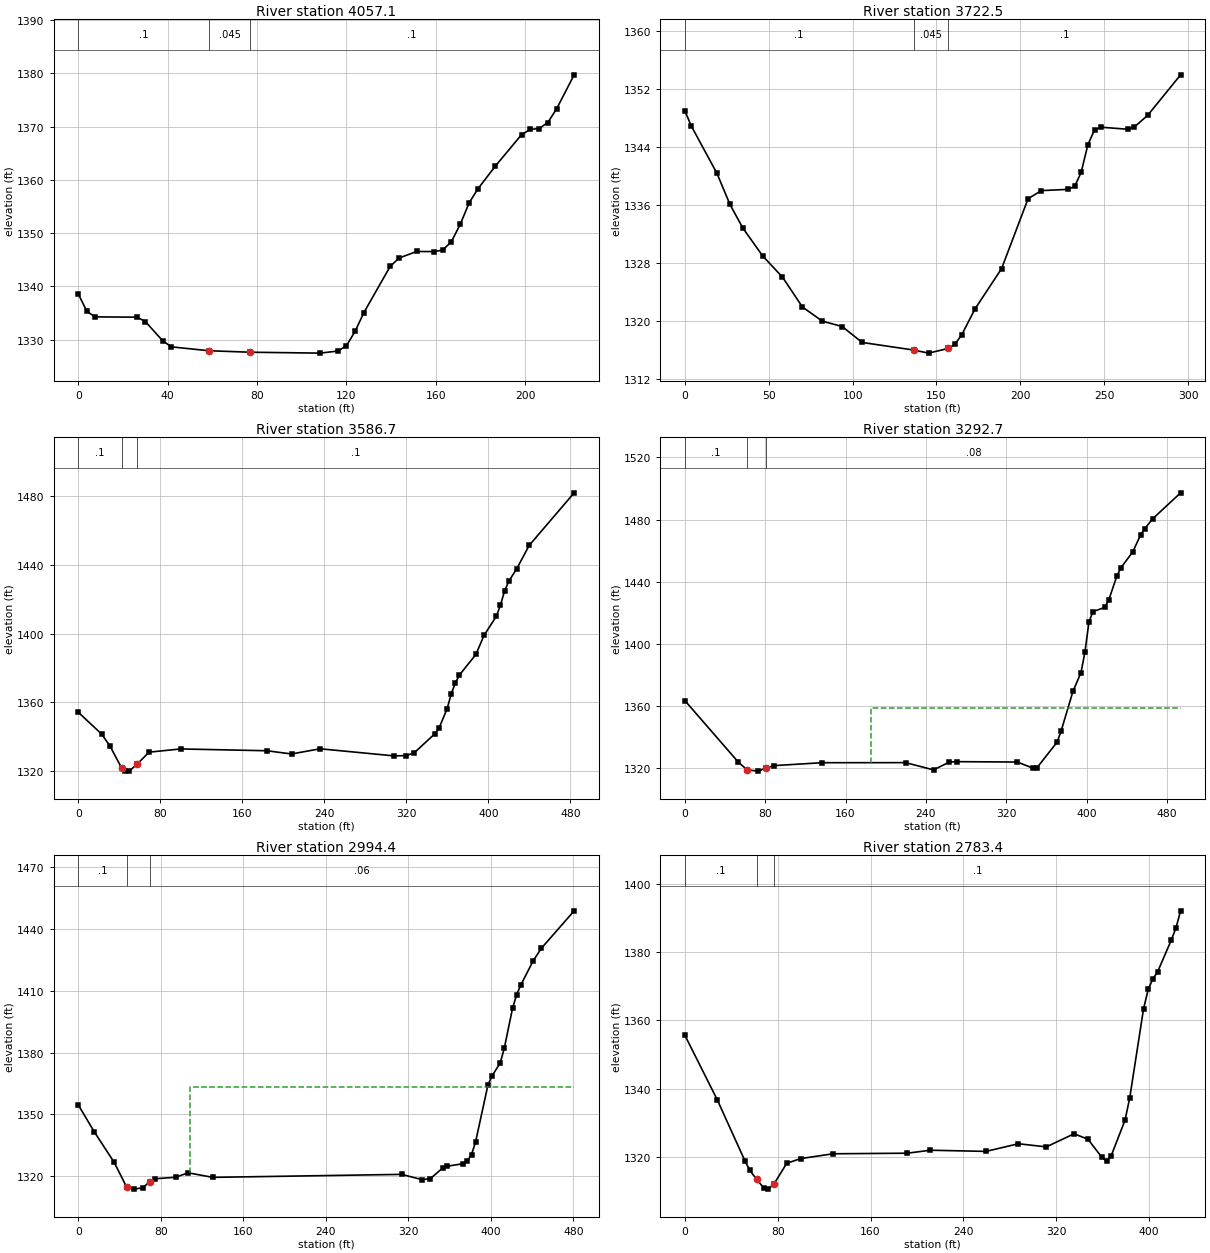
Type RM Length L Ch R = 1 ,4057.1  ,344.7,334.6,325.2
XS GIS Cut Line= 3
     1799050.317      326475.535     1799065.942      326505.483
     1799153.181      326672.149
#Sta/Elev= 30
       0 1338.57     3.8 1335.33     7.5 1334.28    26.3 1334.22      30  1333.4
    37.7 1329.81    41.6 1328.65    58.4 1327.92    76.9 1327.64   108.2 1327.47
   116.1 1327.86     120 1328.86   123.9 1331.59   127.8 1335.09   139.6 1343.78
   143.5 1345.32   151.4 1346.56   159.2 1346.54   163.1 1346.82     167 1348.43
     171 1351.74   174.9 1355.69   178.8 1358.31   186.6 1362.58   198.4 1368.52
   202.3  1369.5   206.2 1369.65   210.1 1370.77   214.1 1373.39   221.9 1379.74
#Mann= 3 , 0 , 0
       0      .1       0    58.4    .045       0    76.9      .1       0
Bank Sta=58.4,76.9
XS Rating Curve= 0 ,0
Exp/Cntr=0.3,0.1

Type RM Length L Ch R = 1 ,3722.5  ,137.6,135.8,130
XS GIS Cut Line= 4
     1798713.077       326622.67     1798746.931      326640.899
     1798866.723      326750.274     1798931.827      326819.285
#Sta/Elev= 30
       0 1349.04     3.8 1346.96    19.2 1340.38    26.9 1336.12    34.6 1332.86
    46.4 1329.02    58.2  1326.1    70.1 1321.98      82 1320.02    93.8 1319.29
   105.7 1317.09   136.3 1316.05   145.3 1315.62   157.1 1316.27   161.1 1316.88
   165.1 1318.17     173 1321.73   188.8 1327.27   204.6 1336.91   212.5 1338.02
   228.3 1338.19   232.3 1338.59   236.2 1340.52   240.2 1344.33   244.2  1346.4
   248.1 1346.76   263.9 1346.48   267.9 1346.79   275.8 1348.38   295.5 1353.98
#Mann= 3 , 0 , 0
       0      .1       0   136.3    .045       0   157.1      .1       0
Bank Sta=136.3,157.1
XS Rating Curve= 0 ,0
Exp/Cntr=0.3,0.1

Type RM Length L Ch R = 1 ,3586.7  ,282.5,293.9,304.1
XS GIS Cut Line= 3
     1798660.994      326738.555     1798743.025      326780.222
     1798959.171      327107.045
#Sta/Elev= 30
       0 1354.26      23 1341.41    30.7 1334.72    42.2 1321.89      46 1319.98
    49.8 1320.03    57.5 1324.12      69 1331.04     100 1332.91     184 1331.85
     208 1329.98   235.9    1333   307.9 1328.87   319.9    1329   327.9 1330.72
   347.9 1341.77   351.9 1344.93   359.9 1356.46   363.9 1365.12   367.9 1371.39
   371.9 1375.99   387.9 1387.97   395.9 1399.11   407.9 1410.24   411.9 1416.78
   415.9 1424.93   419.9 1430.52   427.9 1438.04   439.9 1451.49   483.8 1482.14
#Mann= 3 , 0 , 0
       0      .1       0    42.2    .045       0    57.5      .1       0
Bank Sta=42.2,57.5
XS Rating Curve= 0 ,0
Exp/Cntr=0.3,0.1

Type RM Length L Ch R = 1 ,3292.7  ,302.1,298.3,294.1
XS GIS Cut Line= 3
     1798478.702      326923.451      1798502.14      326957.305
     1798766.463      327324.493
#Sta/Elev= 30
       0 1363.62    53.1 1324.12      62 1319.03    72.9 1318.21    80.9 1320.22
    88.8 1321.75   136.4 1323.62   219.8 1323.67   247.6    1319   263.4 1324.04
   271.4 1324.29   330.9 1324.06   346.8 1320.09   350.7 1320.46   370.6 1336.83
   374.6 1343.93   386.4 1369.49   394.4 1381.53   398.4 1394.93   402.3    1414
   406.3  1420.8   418.2 1423.48   422.2 1428.54   430.1 1443.58   434.1 1448.88
     446 1459.24   453.9 1470.31   457.9 1474.08   465.8 1480.48   493.6 1497.15
#Mann= 3 , 0 , 0
       0      .1       0      62    .045       0    80.9     .08       0
#XS Ineff= 2 , 0
                          185.56         1358.67
Permanent Ineff=
       F       F
Bank Sta=62,80.9
XS Rating Curve= 0 ,0
Exp/Cntr=0.3,0.1

Type RM Length L Ch R = 1 ,2994.4  ,211.8,211,209.2
XS GIS Cut Line= 3
     1798246.931       327122.67     1798272.973      327151.316
     1798589.379       327459.91
#Sta/Elev= 30
       0 1354.53    15.5  1341.5    34.8 1326.67    46.7 1314.82    54.4 1313.72
    62.6 1314.42    69.4  1317.4    74.6 1318.75    94.5 1319.49   106.4 1321.64
   130.3 1319.43   313.5 1320.88   333.4  1318.3   341.3 1318.82   353.3    1324
   357.3 1324.82   373.2 1326.06   377.2 1327.55   381.2 1330.52   385.1 1336.56
   397.1 1364.23     401 1368.58     409 1374.95     413 1382.17     421 1401.57
     425 1408.16   428.9 1412.71   440.9 1424.44   448.8 1430.53   480.7 1448.77
#Mann= 3 , 0 , 0
       0      .1       0    46.7    .045       0    69.4     .06       0
#XS Ineff= 2 , 0
                          108.06         1363.47
Permanent Ineff=
       F       F
Bank Sta=46.7,69.4
XS Rating Curve= 0 ,0
Exp/Cntr=0.3,0.1

Type RM Length L Ch R = 1 ,2783.4  ,197.2,196.2,194.8
XS GIS Cut Line= 2
     1798112.817      327288.035     1798433.129      327570.587
#Sta/Elev= 30
       0 1355.65    27.9 1336.74    51.9 1318.72    55.9 1316.06    61.8  1313.4
    67.9 1310.91    71.8 1310.51    76.8 1312.01    87.8 1318.08    99.8 1319.46
   127.7 1320.87   191.6 1321.04   211.6 1321.91   259.5 1321.57   287.4 1323.81
   311.4 1322.89   335.3 1326.73   347.3 1325.13   359.3 1319.81   363.3  1318.7
   367.2 1320.21   379.2 1330.72   383.2 1337.13   395.2 1363.43   399.2 1369.04
   403.2 1372.15   407.2 1374.14   419.1 1383.53   423.1 1387.09   427.1 1392.07
#Mann= 3 , 0 , 0
       0      .1       0    61.8    .045       0    76.8      .1       0
Bank Sta=61.8,76.8
XS Rating Curve= 0 ,0
Exp/Cntr=0.3,0.1