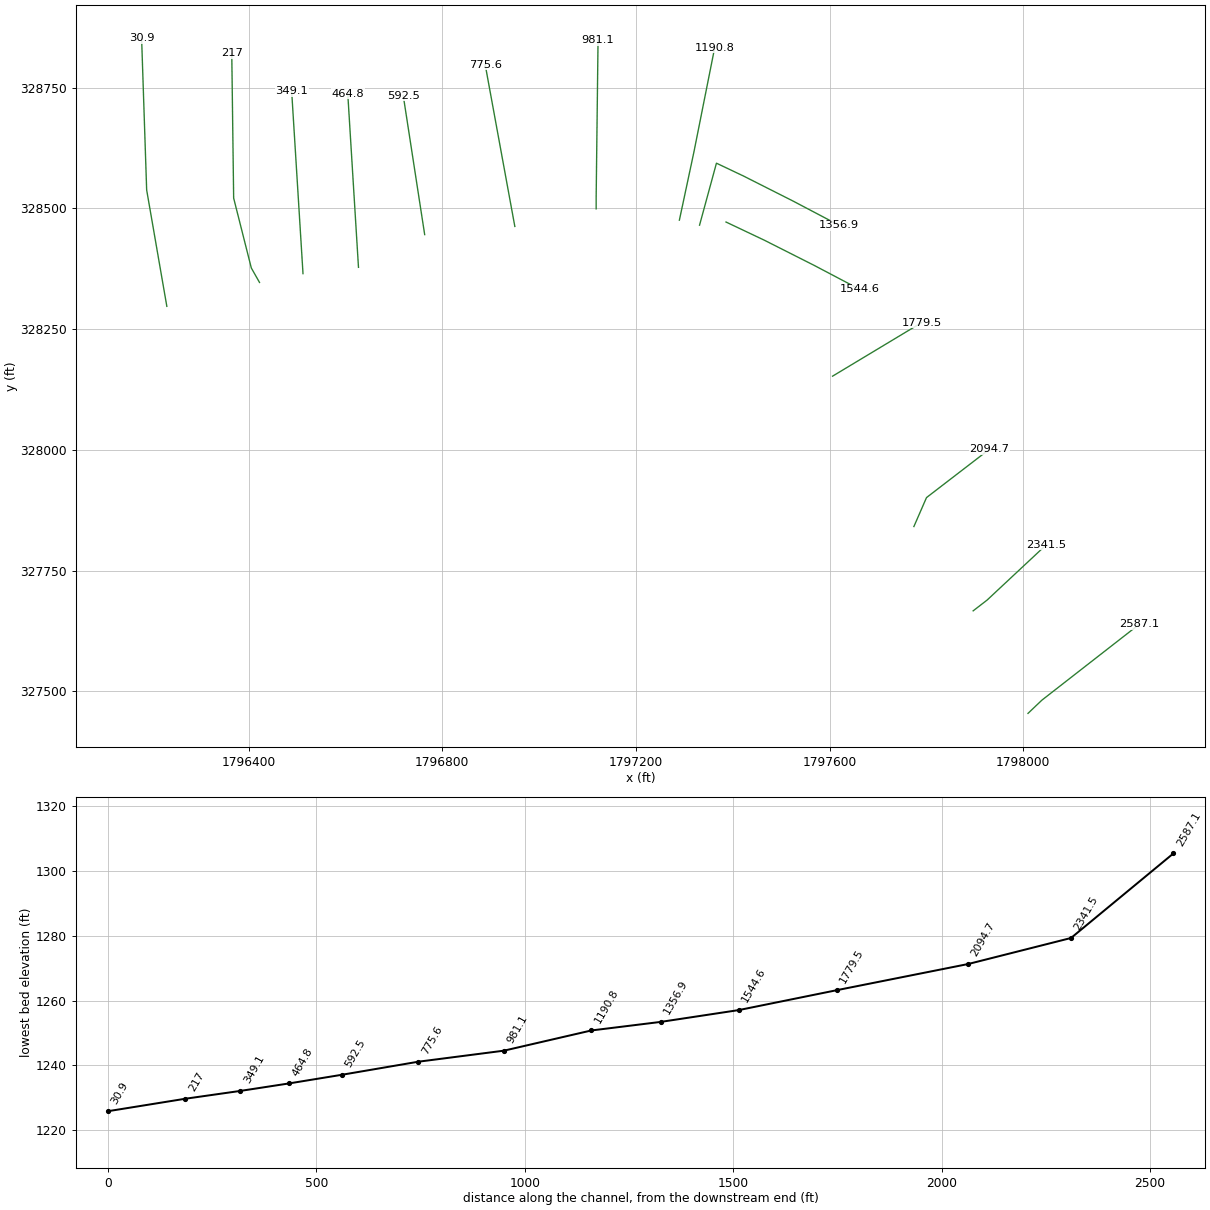
HEC-RAS study MATTSCK.prj: MATTSCK

--- MATTSCK.g01 (geometry) --- (continued)

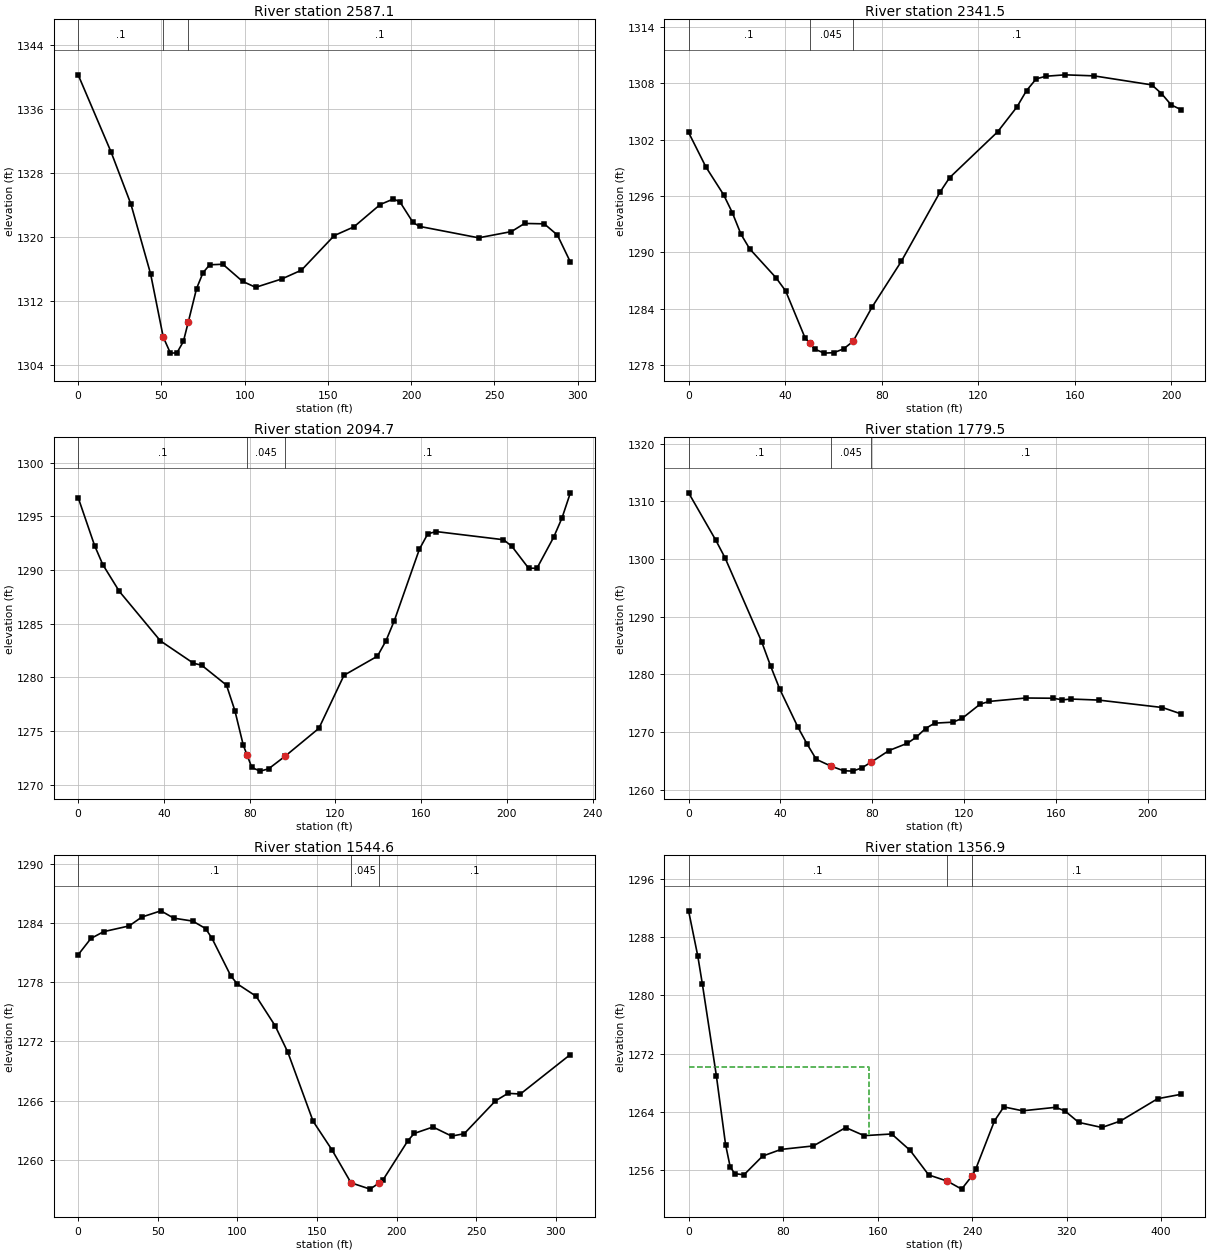
Type RM Length L Ch R = 1 ,2587.1  ,242.9,245.7,246
XS GIS Cut Line= 3
     1798009.952      327454.701     1798038.598      327482.045
     1798240.421      327639.597
#Sta/Elev= 30
       0 1340.28    19.8  1330.6    31.7 1324.08    43.5 1315.36    51.1 1307.44
    55.4 1305.43    59.3 1305.46    63.2 1306.89    66.1 1309.29    71.1 1313.51
      75 1315.51      79 1316.49    86.9 1316.56    98.7 1314.42   106.6 1313.67
   122.3 1314.72   134.1 1315.82   153.8 1320.15   165.6 1321.24   181.4 1324.04
   189.3 1324.73   193.2 1324.38   201.1 1321.79     205  1321.3   240.5 1319.87
   260.2 1320.65   268.1 1321.67   279.9 1321.62   287.8 1320.22   295.6 1316.84
#Mann= 3 , 0 , 0
       0      .1       0    51.1    .045       0    66.1      .1       0
Bank Sta=51.1,66.1
XS Rating Curve= 0 ,0
Exp/Cntr=0.3,0.1

Type RM Length L Ch R = 1 ,2341.5  ,247.8,246.8,244.3
XS GIS Cut Line= 3
     1797896.671      327666.941     1797925.317      327689.076
     1798047.713       327803.66
#Sta/Elev= 30
       0 1302.75     7.2 1299.07    14.5 1296.14    18.1 1294.24    21.7 1291.94
    25.3 1290.39    36.2 1287.32    40.2 1285.92    48.2 1280.96    50.2 1280.35
    52.2 1279.74    56.2 1279.31    60.2 1279.36    64.2 1279.76    68.1 1280.55
    76.1 1284.24    88.1 1289.05   104.1 1296.39   108.1 1297.94     128 1302.81
     136 1305.45     140  1307.2     144 1308.44     148 1308.72     156 1308.87
   167.9 1308.76   191.9  1307.8   195.9 1306.88   199.9 1305.68   203.9 1305.18
#Mann= 3 , 0 , 0
       0      .1       0    50.2    .045       0    68.1      .1       0
Bank Sta=50.2,68.1
XS Rating Curve= 0 ,0
Exp/Cntr=0.3,0.1

Type RM Length L Ch R = 1 ,2094.7  ,317.5,315.1,311.6
XS GIS Cut Line= 3
     1797774.275       327841.42     1797800.317      327901.316
     1797930.525      328001.576
#Sta/Elev= 30
       0 1296.76     7.7 1292.27    11.5 1290.51    19.2 1288.02    38.4  1283.4
    53.8 1281.32    57.6 1281.14    69.2 1279.28    73.1 1276.91      77 1273.71
    78.8 1272.76      81 1271.61    84.9 1271.27    88.8 1271.48    96.6 1272.67
   112.3 1275.26     124  1280.2   139.6 1281.98   143.6 1283.42   147.5  1285.3
   159.2 1291.96   163.1 1293.38     167 1293.59   198.4 1292.83   202.3 1292.22
   210.1 1290.18     214 1290.17   221.8 1293.06   225.7 1294.86   229.6  1297.2
#Mann= 3 , 0 , 0
       0      .1       0    78.8    .045       0    96.6      .1       0
Bank Sta=78.8,96.6
XS Rating Curve= 0 ,0
Exp/Cntr=0.3,0.1

Type RM Length L Ch R = 1 ,1779.5  ,286,234.9,198.3
XS GIS Cut Line= 2
     1797606.306      328152.618       1797789.9      328263.295
#Sta/Elev= 30
       0 1311.45    11.9  1303.2    15.9 1300.16    31.8 1285.66    35.7 1281.44
    39.7 1277.42    47.6 1270.83    51.6  1267.9    55.6 1265.24      62 1264.06
    67.5 1263.26    71.5 1263.19    75.4 1263.74    79.4 1264.71    87.3 1266.76
    95.3 1268.02    99.2 1269.09   103.2 1270.58   107.2 1271.51   115.1 1271.68
   119.1 1272.32     127 1274.81     131 1275.28   146.9 1275.87   158.8 1275.83
   162.8 1275.55   166.7 1275.69   178.6 1275.51   206.4 1274.22   214.4 1273.13
#Mann= 3 , 0 , 0
       0      .1       0      62    .045       0    79.4      .1       0
Bank Sta=62,79.4
XS Rating Curve= 0 ,0
Exp/Cntr=0.3,0.1

Type RM Length L Ch R = 1 ,1544.6  ,201,187.7,194.1
XS GIS Cut Line= 4
     1797386.254      328471.628     1797465.681      328433.868
     1797568.546      328381.785     1797662.296      328332.305
#Sta/Elev= 30
       0 1280.78       8 1282.43      16 1283.12      32  1283.7      40  1284.6
      52 1285.23      60 1284.49      72 1284.19      80 1283.44      84 1282.47
    95.9 1278.64    99.9 1277.84   111.8 1276.58   123.7  1273.6   131.7 1270.92
   147.6 1263.92   159.5 1261.01   171.4 1257.69   183.4 1257.05     189 1257.67
   191.3 1257.93   207.2 1261.97   211.1 1262.69   222.9 1263.34   234.6 1262.42
   242.5 1262.66   262.1 1265.98     270 1266.75   277.8 1266.68   309.2 1270.68
#Mann= 3 , 0 , 0
       0      .1       0   171.4    .045       0     189      .1       0
Bank Sta=171.4,189
XS Rating Curve= 0 ,0
Exp/Cntr=0.3,0.1

Type RM Length L Ch R = 1 ,1356.9  ,82.1,166.1,214.5
XS GIS Cut Line= 5
     1797331.567      328465.118     1797366.442      328593.432
     1797422.713       328566.68     1797525.577      328514.597
     1797619.327      328465.118
#Sta/Elev= 30
       0 1291.59     7.8 1285.37    11.7  1281.5    23.5 1268.97    31.3 1259.51
    35.2 1256.45    39.1 1255.51    46.9 1255.36    62.6 1257.92    78.2 1258.84
   105.6 1259.32     133 1261.84   148.6 1260.73   171.9 1260.96   187.5 1258.71
   203.2 1255.34   219.1 1254.48   231.1 1253.39   239.8 1255.19     243 1256.13
   258.9 1262.76   266.8 1264.68   282.7 1264.14   310.6 1264.62   318.4 1264.14
   330.2 1262.55   349.8 1261.85   365.5 1262.74     397  1265.8   416.6  1266.4
#Mann= 3 , 0 , 0
       0      .1       0   219.1    .045       0   239.8      .1       0
#XS Ineff= 2 , 0
          152.35 1270.09
Permanent Ineff=
       F       F
Bank Sta=219.1,239.8
XS Rating Curve= 0 ,0
Exp/Cntr=0.3,0.1

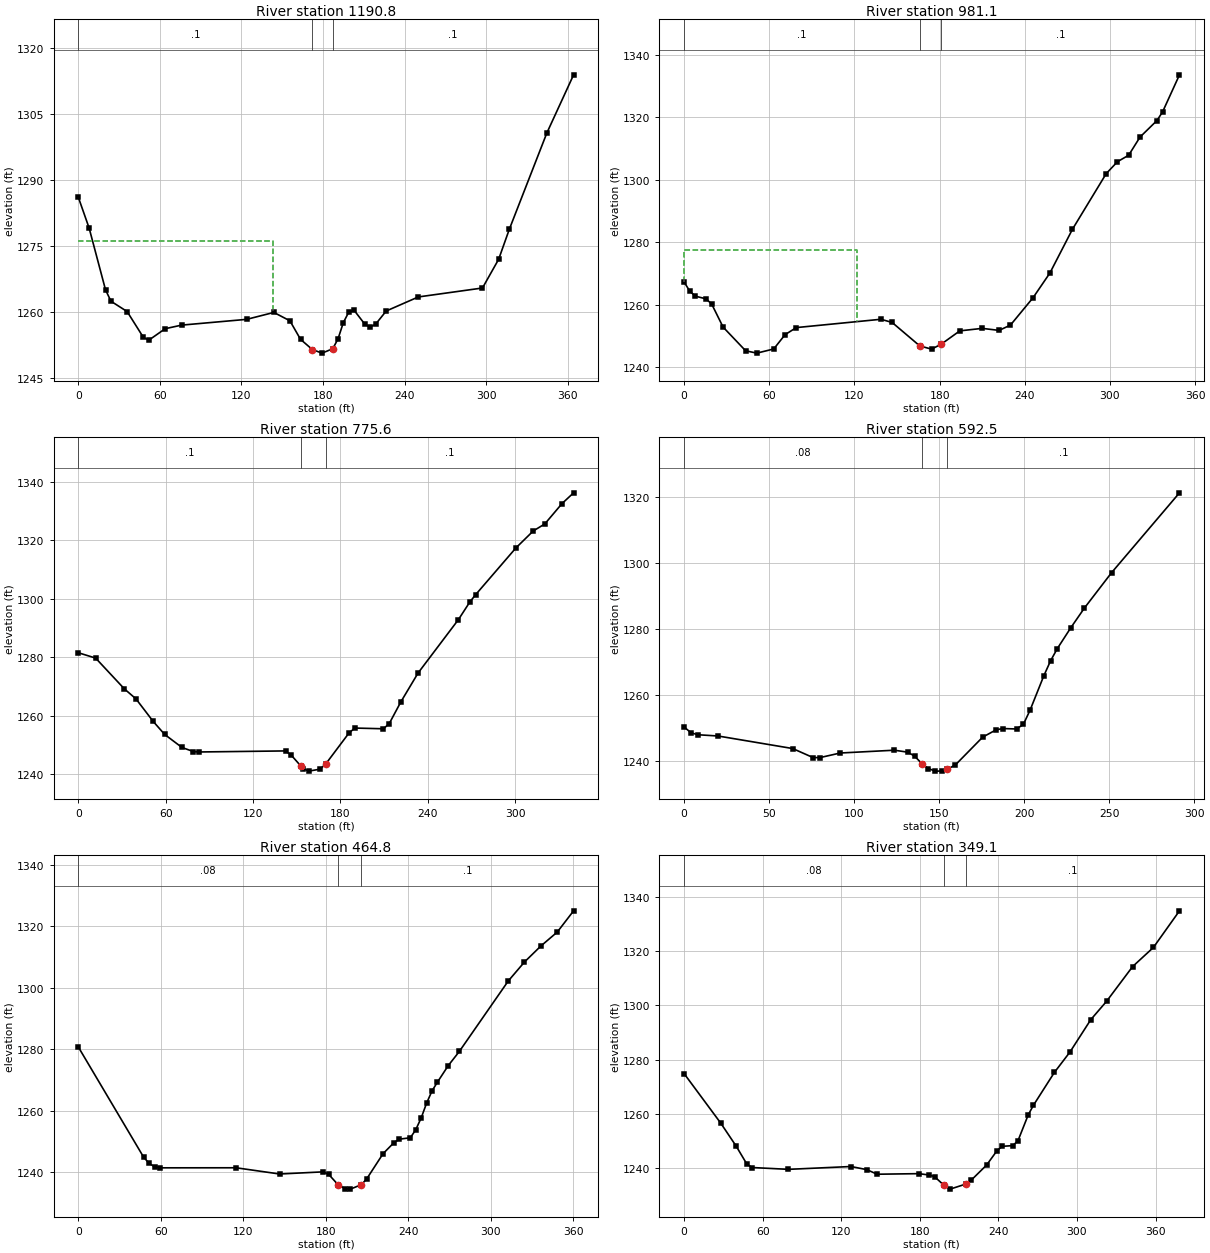
Type RM Length L Ch R = 1 ,1190.8  ,205.6,209.7,213.8
XS GIS Cut Line= 3
       1797289.9      328475.535     1797319.848       328616.16
     1797362.817      328832.305
#Sta/Elev= 30
       0 1286.11       8 1279.07      20 1265.12      24 1262.52    35.9 1260.18
    47.9  1254.3    51.9  1253.7    63.9 1256.29    75.9  1257.1   123.8 1258.41
   143.8 1259.98   155.6 1258.08   163.4 1253.88   172.1 1251.56   179.2 1250.75
   187.1 1251.74     191    1254   194.9 1257.69   198.9 1260.06   202.8 1260.47
   210.7  1257.3   214.6 1256.66   218.6  1257.3   226.4  1260.3     250 1263.49
   297.2 1265.52   309.1 1272.04   316.9 1278.81   344.5 1300.65   364.2 1313.86
#Mann= 3 , 0 , 0
       0      .1       0   172.1    .045       0   187.1      .1       0
#XS Ineff= 2 , 0
          143.14 1276.07
Permanent Ineff=
       F       F
Bank Sta=172.1,187.1
XS Rating Curve= 0 ,0
Exp/Cntr=0.3,0.1

Type RM Length L Ch R = 1 ,981.1   ,201.1,205.4,209.8
XS GIS Cut Line= 3
     1797118.025      328498.972     1797118.025       328522.41
     1797121.931       328847.93
#Sta/Elev= 30
       0 1267.22     3.9 1264.35     7.8 1262.74    15.6 1261.85    19.5  1260.1
    27.4 1252.85    43.3 1245.26    51.2 1244.51    63.1 1245.84    71.1 1250.42
      79 1252.68   138.6 1255.34   146.5 1254.33     166 1246.82   174.3 1245.79
     181 1247.33   194.2 1251.63     210 1252.43   221.9 1251.78   229.9 1253.48
   245.8 1262.22   257.7 1270.14   273.6 1284.15   297.4 1301.95   305.3 1305.75
   313.2 1307.82   321.2 1313.63   333.1  1318.9   337.1 1321.69     349 1333.54
#Mann= 3 , 0 , 0
       0      .1       0     166    .045       0     181      .1       0
#XS Ineff= 2 , 0
          121.83 1277.37
Permanent Ineff=
       F       F
Bank Sta=166,181
XS Rating Curve= 0 ,0
Exp/Cntr=0.3,0.1

Type RM Length L Ch R = 1 ,775.6   ,183.4,183.1,182.1
XS GIS Cut Line= 2
     1796950.056      328462.514     1796888.858      328797.149
#Sta/Elev= 30
       0 1281.58    11.9 1279.75    31.6 1269.24    39.6 1265.81    51.4 1258.12
    59.3 1253.65    71.2 1249.19    79.1 1247.78    83.1 1247.65   142.4 1248.01
   146.4 1246.48   152.8 1242.88   154.3 1241.99   158.2  1241.1   166.1 1241.77
   170.1 1243.64   185.9 1254.12   189.9 1255.83   209.6 1255.58   213.6 1257.38
   221.5 1264.74   233.4 1274.67   261.1 1292.92     269 1298.99   272.9 1301.43
   300.6 1317.43   312.5 1323.23   320.4 1325.61   332.3 1332.61   340.2 1336.26
#Mann= 3 , 0 , 0
       0      .1       0   152.8    .045       0   170.1      .1       0
Bank Sta=152.8,170.1
XS Rating Curve= 0 ,0
Exp/Cntr=0.3,0.1

Type RM Length L Ch R = 1 ,592.5   ,129.6,127.7,125.4
XS GIS Cut Line= 2
     1796763.858      328445.587     1796719.588      328733.347
#Sta/Elev= 30
       0 1250.39       4 1248.66       8 1248.06    19.9 1247.68    63.8 1243.89
    75.8 1241.16    79.8 1241.15    91.7 1242.54   123.6 1243.39   131.6 1242.78
   135.6 1241.54   139.8 1239.29   143.6 1237.84   147.6 1237.07   151.6 1237.09
   154.8 1237.67   159.5 1238.97   175.5 1247.34   183.5 1249.57   187.4 1249.93
   195.4  1249.8   199.4 1251.17   203.4 1255.53   211.4 1265.81   215.4 1270.38
   219.4  1274.1   227.3 1280.37   235.3 1286.32   251.3 1297.02   291.2 1321.12
#Mann= 3 , 0 , 0
       0     .08       0   139.8    .045       0   154.8      .1       0
Bank Sta=139.8,154.8
XS Rating Curve= 0 ,0
Exp/Cntr=0.3,0.1

Type RM Length L Ch R = 1 ,464.8   ,115.7,115.7,115.7
XS GIS Cut Line= 2
      1796627.14      328377.878     1796605.004      328737.253
#Sta/Elev= 30
       0 1280.71    47.5 1244.79    51.4 1242.82    55.4 1241.67    59.4 1241.32
   114.7 1241.34   146.4 1239.31     178 1240.01     182  1239.2   188.8 1235.85
   193.9 1234.55   197.8 1234.38   205.8 1235.83   209.7 1237.73   221.6 1245.95
   229.5 1249.53   233.4 1250.66   241.4 1251.12   245.3 1253.71   249.3 1257.59
   253.2 1262.38   257.2 1266.42   261.1 1269.25     269 1274.66     277 1279.24
   312.6 1302.22   324.4 1308.41   336.3 1313.61   348.2 1318.15   360.1 1325.08
#Mann= 3 , 0 , 0
       0     .08       0   188.8    .045       0   205.8      .1       0
Bank Sta=188.8,205.8
XS Rating Curve= 0 ,0
Exp/Cntr=0.3,0.1

Type RM Length L Ch R = 1 ,349.1   ,133.2,132.1,130.9
XS GIS Cut Line= 2
     1796512.556      328364.858     1796489.119      328742.462
#Sta/Elev= 30
       0 1274.75    27.9  1256.5    39.8 1247.91    47.8  1241.4    51.8 1240.08
    79.6  1239.4   127.4 1240.45   139.4  1239.3   147.4  1237.6   179.2 1237.81
   187.2 1237.31   191.2 1236.72   198.1 1233.65   203.1 1232.09     215 1233.95
     219 1235.29     231    1241     239 1246.34   242.9 1247.91   250.9 1248.17
   254.9 1249.92   262.8 1259.57   266.8 1263.12   282.8 1275.26   294.7  1282.8
   310.6 1294.76   322.6 1301.51   342.5 1314.35   358.4 1321.43   378.3 1334.96
#Mann= 3 , 0 , 0
       0     .08       0   198.1    .045       0     215      .1       0
Bank Sta=198.1,215
XS Rating Curve= 0 ,0
Exp/Cntr=0.3,0.1

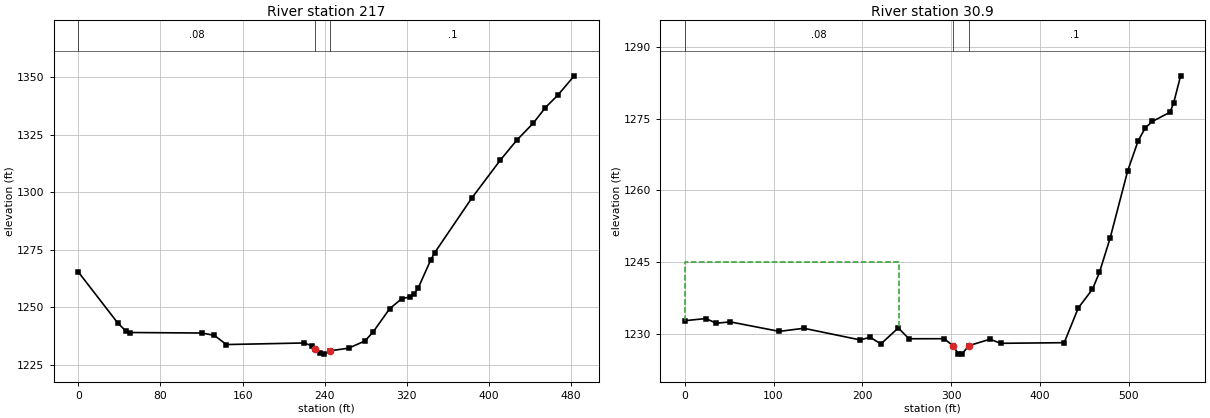
Type RM Length L Ch R = 1 ,217     ,185.4,186.1,186.4
XS GIS Cut Line= 4
     1796422.713      328346.628     1796405.786      328376.576
     1796369.327      328521.108     1796365.421      328820.587
#Sta/Elev= 30
       0 1265.36    38.3 1243.25    46.2 1239.73    50.1 1239.06   120.7 1238.84
   132.5  1237.8   144.2 1233.83   219.4 1234.51   227.4 1233.36   230.6 1232.01
   235.4 1230.13   239.4 1229.67   245.6 1231.13   263.3 1232.26   279.3 1235.43
   287.3  1239.4   303.3 1249.44   315.2  1253.8   323.2 1254.51   327.2 1255.83
   331.2 1258.55   343.2 1270.55   347.2  1273.8   383.1 1297.38   411.1    1314
   427.1 1322.63     443 1329.95     455 1336.81     467 1342.15     483 1350.57
#Mann= 3 , 0 , 0
       0     .08       0   230.6    .045       0   245.6      .1       0
Bank Sta=230.6,245.6
XS Rating Curve= 0 ,0
Exp/Cntr=0.3,0.1

Type RM Length L Ch R = 1 ,30.9    ,29.3,30.9,32.5
XS GIS Cut Line= 3
     1796231.306      328297.149      1796189.64      328538.035
     1796179.223      328851.837
#Sta/Elev= 30
       0 1232.79    23.7 1233.24    35.5 1232.27    51.3 1232.54   106.5 1230.56
   134.1 1231.21   197.2 1228.79     209 1229.32   220.8 1227.93   240.5 1231.28
   252.4 1229.02   292.2 1229.03   302.3 1227.52     308 1225.92     312 1225.81
     320 1227.59   343.8 1228.92   355.7 1228.07   427.3  1228.2   443.2 1235.47
   459.1 1239.36     467 1242.88     479 1250.03   498.8  1264.1   510.7 1270.43
   518.7 1273.08   526.6 1274.41   546.5 1276.34   550.5 1278.26   558.4 1283.94
#Mann= 3 , 0 , 0
       0     .08       0   302.3    .045       0     320      .1       0
#XS Ineff= 2 , 0
          241.28 1245.09
Permanent Ineff=
       F       F
Bank Sta=302.3,320
XS Rating Curve= 0 ,0
Exp/Cntr=0.3,0.1

Chan Stop Cuts=-1
Use User Specified Reach Order=0
Composite Channel Slope=5